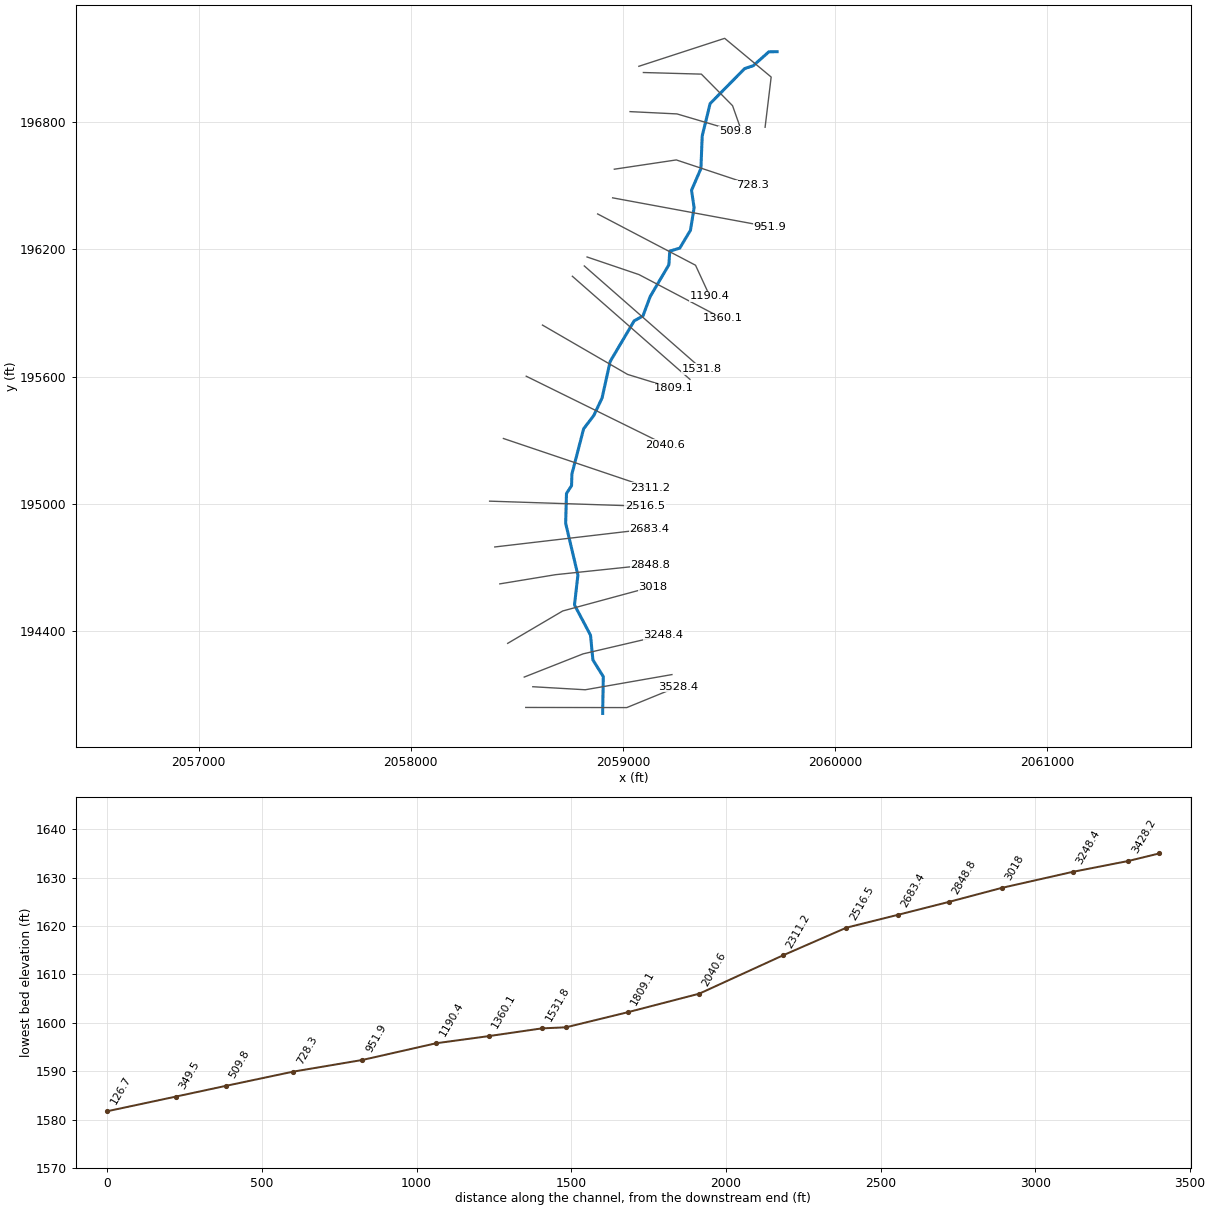
--- INDIANCKT3.prj (project) ---

Proj Title=INDIANCKT3
Current Plan=p01
Default Exp/Contr=0,0
English Units
Geom File=g01
Flow File=f01
Plan File=p01
BEGIN DESCRIPTION:
END DESCRIPTION:
DSS Export Rating Curves= 0
DSS Export Rating Curve Sorted= 0
DSS Export Volume Flow Curves= 0
DXF OffsetX= 0
DXF OffsetY= 0
DXF ScaleX= 0
DXF ScaleY= 0

--- INDIANCKT3.p01 (plan) ---

Plan Title=Floodplain
Program Version=4.00
Geom File=g01
Flow File=f01
K Sum by GR=0
Std Step Tol=0.01
Critical Tol=0.01
Num of Std Step Trials=20
Max Error Tol=0.3
Flow Tol Ratio=0.001
Split Flow NTrial=30
Split Flow Tol=0.02
Split Flow Ratio=0.02
Log Output Level=0
Friction Slope Method=1
Unsteady Friction Slope Method=2
Unsteady Bridges Friction Slope Method=1
Global Log Level=0
CheckData=False
Run HTab=0
Run UNet=0
Run PostProcess=0
UNET Theta=0
UNET Theta Warmup=0
UNET ZTol=0
UNET ZSATol=0
UNET MxIter=0
UNET MaxInSteps=0
UNET DtIC=0
UNET DtMin=0
UNET MaxCRTS=0
UNET WFStab=0
UNET SFStab=0
UNET WFX=0
UNET SFX=0
UNET DSS MLevel=0
UNET DZMax Abort=0
UNET Convert EG Bridges=0
UNET Use Existing IB Tables=0
UNET Froude Limit=0
UNET Froude Power=0
Write IC File=0
Echo Input=False
Echo Output=False
Write Detailed=0

--- INDIANCKT3.f01 (steady flow) ---

Flow Title=NFF Regression Equation
Program Version=4.10
Number of Profiles= 1
Profile Names=P100yr
River Rch & RM=INDIANCKT3,Main            ,3528.4
530.5168
River Rch & RM=INDIANCKT3,Main            ,2848.8
 535.524
River Rch & RM=INDIANCKT3,Main            ,2311.2
592.4487
River Rch & RM=INDIANCKT3,Main            ,728.3
607.5327
River Rch & RM=INDIANCKT3,Main            ,509.8
612.2317
Boundary for River Rch & Prof#=INDIANCKT3,Main            , 1
Up Type= 0
Dn Type= 3
Dn Slope=0.013609
DSS Import GetInterval= 0
DSS Import GetPeak= 0
DSS Import FillOption= 0

--- INDIANCKT3.g01 (geometry) ---

Geom Title=USGS 10m DEM
Program Version=4.10

River Reach=INDIANCKT3      ,Main
Reach XY= 30
     2058904.902      194011.231      2058907.94      194184.409
     2058858.895      194263.402      2058847.61      194380.155
     2058772.089       194522.95     2058788.148      194663.575
     2058730.423      194907.933     2058734.329      195048.558
     2058758.201       195085.45     2058759.937      195140.572
     2058815.058      195353.245     2058863.669      195417.481
     2058902.298      195499.513     2058940.058      195670.701
     2059053.643      195862.866     2059094.918      195885.876
     2059129.184      195977.715     2059217.306      196127.279
     2059221.372      196191.778     2059268.507      196205.742
     2059319.028      196290.117     2059336.215      196396.367
     2059324.062      196478.832     2059368.333      196581.262
      2059374.41      196734.908     2059411.736      196887.686
     2059574.685        197052.8     2059614.963      197066.341
     2059688.921      197131.966     2059727.403      197132.584

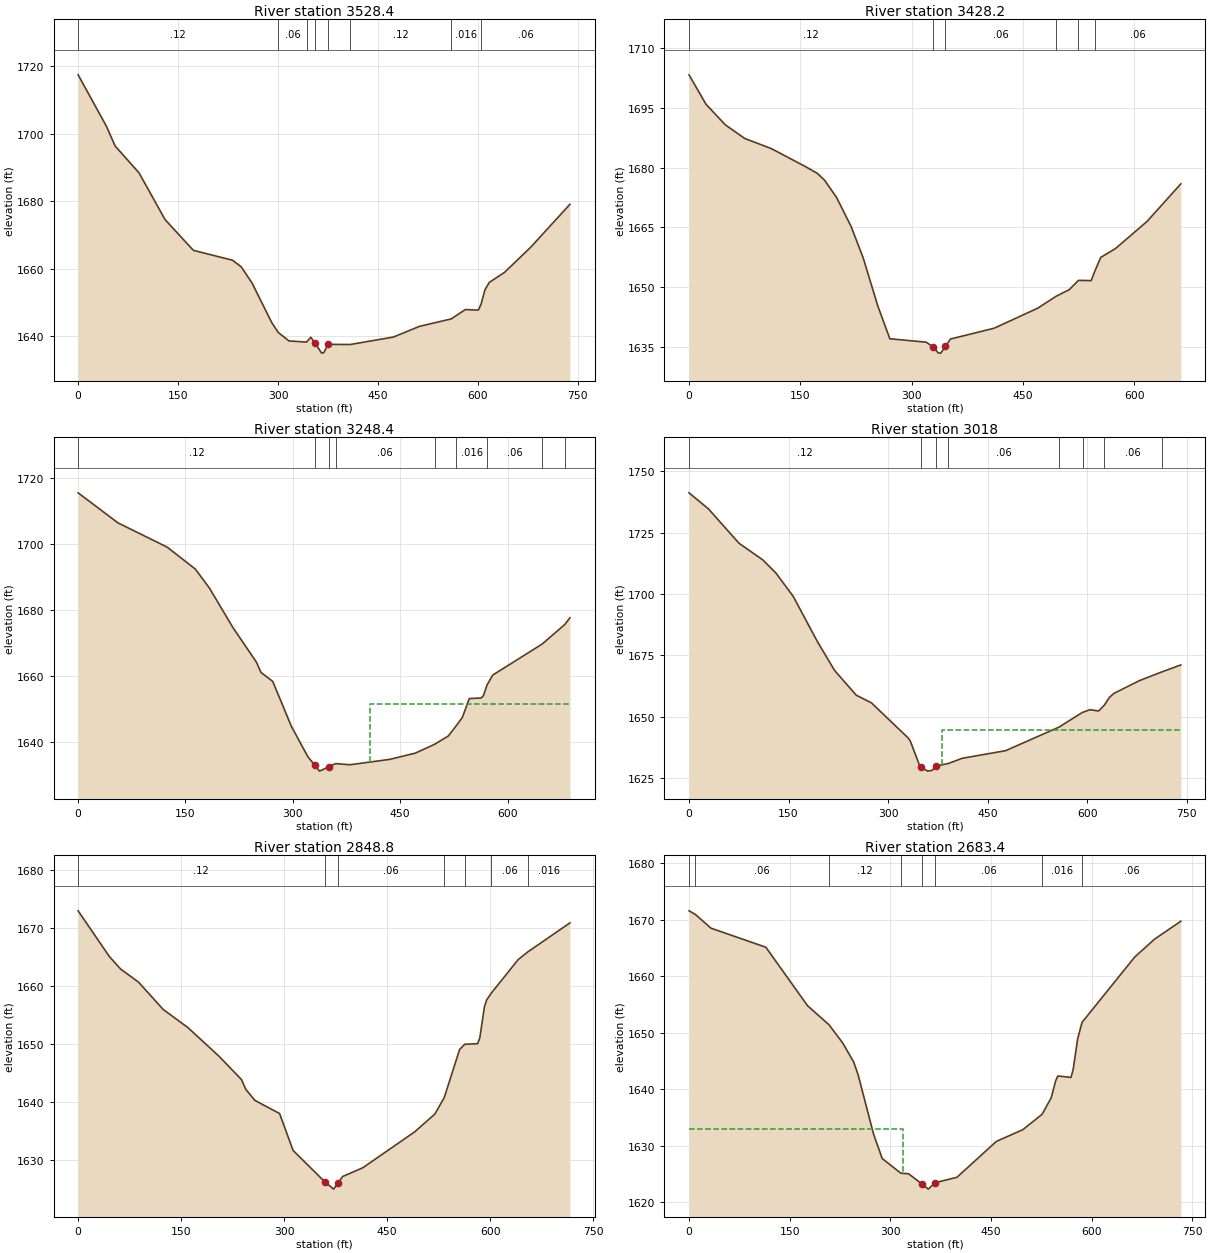
Type RM Length L Ch R = 1 ,3528.4  ,95.6,100.2,103.8
XS GIS Cut Line= 3
     2058542.162       194039.19     2059018.602      194038.543
      2059260.79      194137.501
#Sta/Elev= 30
       0 1717.44    42.4 1702.23    55.5 1696.37    91.4 1688.41   130.5 1674.55
     173 1665.45   231.7 1662.53   244.8 1660.56   261.1 1655.75   290.4 1644.13
   300.31641.134   316.5 1638.62  342.78 1638.28   349.2 1639.72   355.7 1637.95
   365.5 1635.01   368.8 1635.18  375.281637.612  408.391637.563   473.2 1639.77
   512.4 1642.95   559.91645.139   581.1 1647.91   600.7 1647.76  604.871649.563
   610.5 1653.73   617.1 1655.96     640 1658.94   679.2 1666.37   738.1 1679.09
#Mann= 8 ,-1 , 0
       0     .12       0   300.3     .06       0  342.78     .12       0
   355.7    .045       0  375.28     .06       0  408.39     .12       0
   559.9    .016       0  604.87     .06       0
Bank Sta=355.7,375.28
XS Rating Curve= 0 ,0
Exp/Cntr=0.3,0.1

Type RM Length L Ch R = 1 ,3428.2  ,178.5,179.7,180.6
XS GIS Cut Line= 3
      2058575.46      194136.937     2058822.856      194122.614
      2059231.71      194194.229
#Sta/Elev= 30
       0 1703.33    22.8 1695.96    48.9 1690.78      75 1687.36   110.9 1684.81
   156.5 1680.33   172.8 1678.61   182.6 1676.89   198.9 1672.54   218.5 1665.24
   234.8 1657.35   254.4 1645.32   270.7 1637.05   319.7  1636.2   329.5 1634.93
   336.1 1633.48   339.3 1633.45   345.6 1635.14   352.4 1636.99   411.2  1639.7
   470.1 1644.74  494.971647.747   512.6  1649.4  524.96 1651.72     542 1651.66
  547.68 1654.34     555 1657.49   574.6 1659.67   617.1 1666.47   662.9 1675.95
#Mann= 6 ,-1 , 0
       0     .12       0   329.5    .045       0   345.6     .06       0
  494.97     .08       0  524.96    .016       0  547.68     .06       0
Bank Sta=329.5,345.6
XS Rating Curve= 0 ,0
Exp/Cntr=0.3,0.1

Type RM Length L Ch R = 1 ,3248.4  ,229.1,230.5,230.2
XS GIS Cut Line= 3
     2058535.095       194182.51     2058812.439      194291.885
     2059191.345      194380.427
#Sta/Elev= 30
       0 1715.41    55.7 1706.32   124.5 1698.97   163.8 1692.33   183.5 1686.58
   216.2 1674.68     249 1664.22   255.5 1661.07   271.9 1658.36   298.1  1644.7
     321 1635.58   330.8 1632.94   337.4  1631.2   350.4 1632.54  360.021633.477
   379.9 1633.13   435.5 1634.76   471.4 1636.66  498.171639.324   517.2 1641.82
   528.51644.974   536.8 1647.42   546.6 1653.16     563 1653.32   566.3 1654.04
   571.4 1657.26   579.3 1660.26  648.381669.644  680.171675.597   687.2 1677.61
#Mann= 9 ,-1 , 0
       0     .12       0   330.8    .045       0   350.4     .12       0
  360.02     .06       0  498.17     .08       0   528.5    .016       0
   571.4     .06       0  648.38     .12       0  680.17     .08       0
#XS Ineff= 2 , 0
                          407.97         1651.43
Permanent Ineff=
       F       F
Bank Sta=330.8,350.4
XS Rating Curve= 0 ,0
Exp/Cntr=0.3,0.1

Type RM Length L Ch R = 1 ,3018    ,172.2,169.1,165
XS GIS Cut Line= 3
     2058457.007      194341.533     2058716.519      194494.272
     2059141.352       194609.39
#Sta/Elev= 30
       0 1741.23    29.5 1734.63    75.3  1720.7   111.3 1713.89   130.9 1708.58
   157.1 1699.04   193.1 1680.82   219.3 1668.92     252 1658.81   274.9 1655.69
   330.5 1641.33   333.7 1640.01   346.8 1630.68     350 1629.41   359.8 1627.87
   366.3 1628.19   372.8 1629.96  390.89 1630.98     412 1633.11   477.2  1636.2
  557.561645.774  593.121651.802   604.3  1652.9   617.4 1652.36     6261654.747
   633.7 1657.91   640.2  1659.5   679.3 1664.78  713.18 1668.33   741.3 1671.12
#Mann= 8 ,-1 , 0
       0     .12       0     350    .045       0   372.8     .12       0
  390.89     .06       0  557.56     .08       0  593.12    .016       0
     626     .06       0  713.18     .12       0
#XS Ineff= 2 , 0
                          380.78         1644.67
Permanent Ineff=
       F       F
Bank Sta=350,372.8
XS Rating Curve= 0 ,0
Exp/Cntr=0.3,0.1

Type RM Length L Ch R = 1 ,2848.8  ,164.9,165.4,165.4
XS GIS Cut Line= 3
       2058419.9      194622.135     2058683.533      194665.583
     2059130.147      194712.458
#Sta/Elev= 30
       0    1673    45.6  1665.1    61.9 1662.96      88  1660.7   123.8    1656
   159.7 1652.88   205.3 1647.91   237.9  1643.9   244.4 1642.18   257.4 1640.31
   293.4 1638.04   313.1 1631.67     359  1626.3   372.1    1625   378.6 1626.06
   385.2 1627.17   414.7 1628.69   490.1 1634.87   519.6 1637.95  533.241640.796
   555.6 1649.08  562.941649.978   581.9 1650.09   585.1 1651.12   591.7  1656.4
     595 1657.63  601.89 1658.83   640.9 1664.58  654.711665.897   716.3 1670.92
#Mann= 7 ,-1 , 0
       0     .12       0     359    .045       0   378.6     .06       0
  533.24     .08       0  562.94    .016       0  601.89     .06       0
  654.71    .016       0
Bank Sta=359,378.6
XS Rating Curve= 0 ,0
Exp/Cntr=0.3,0.1

Type RM Length L Ch R = 1 ,2683.4  ,170.2,166.9,163.1
XS GIS Cut Line= 2
     2058396.121      194796.242     2059123.844      194881.425
#Sta/Elev= 30
       0 1671.59    9.271670.975    32.7 1668.52   114.5 1665.14   176.6 1654.79
  208.651651.409     229 1648.19   245.3 1644.83   251.9 1642.58   274.8 1632.11
   287.8 1627.74  315.631625.135   327.1 1625.04   346.7 1623.26   356.5 1622.32
   366.4 1623.45   399.1 1624.41   457.9 1630.77   497.2 1632.84  526.031635.564
   539.7 1638.52   546.2  1641.5   549.5 1642.35   569.1  1642.1   572.4 1643.57
     579 1648.93  585.511651.842     664 1663.41   693.4 1666.56   732.7 1669.75
#Mann= 8 ,-1 , 0
       0     .12       0    9.27     .06       0  208.65     .12       0
  315.63     .06       0   346.7    .045       0   366.4     .06       0
  526.03    .016       0  585.51     .06       0
#XS Ineff= 2 , 0
          318.37    1633
Permanent Ineff=
       F       F
Bank Sta=346.7,366.4
XS Rating Curve= 0 ,0
Exp/Cntr=0.3,0.1

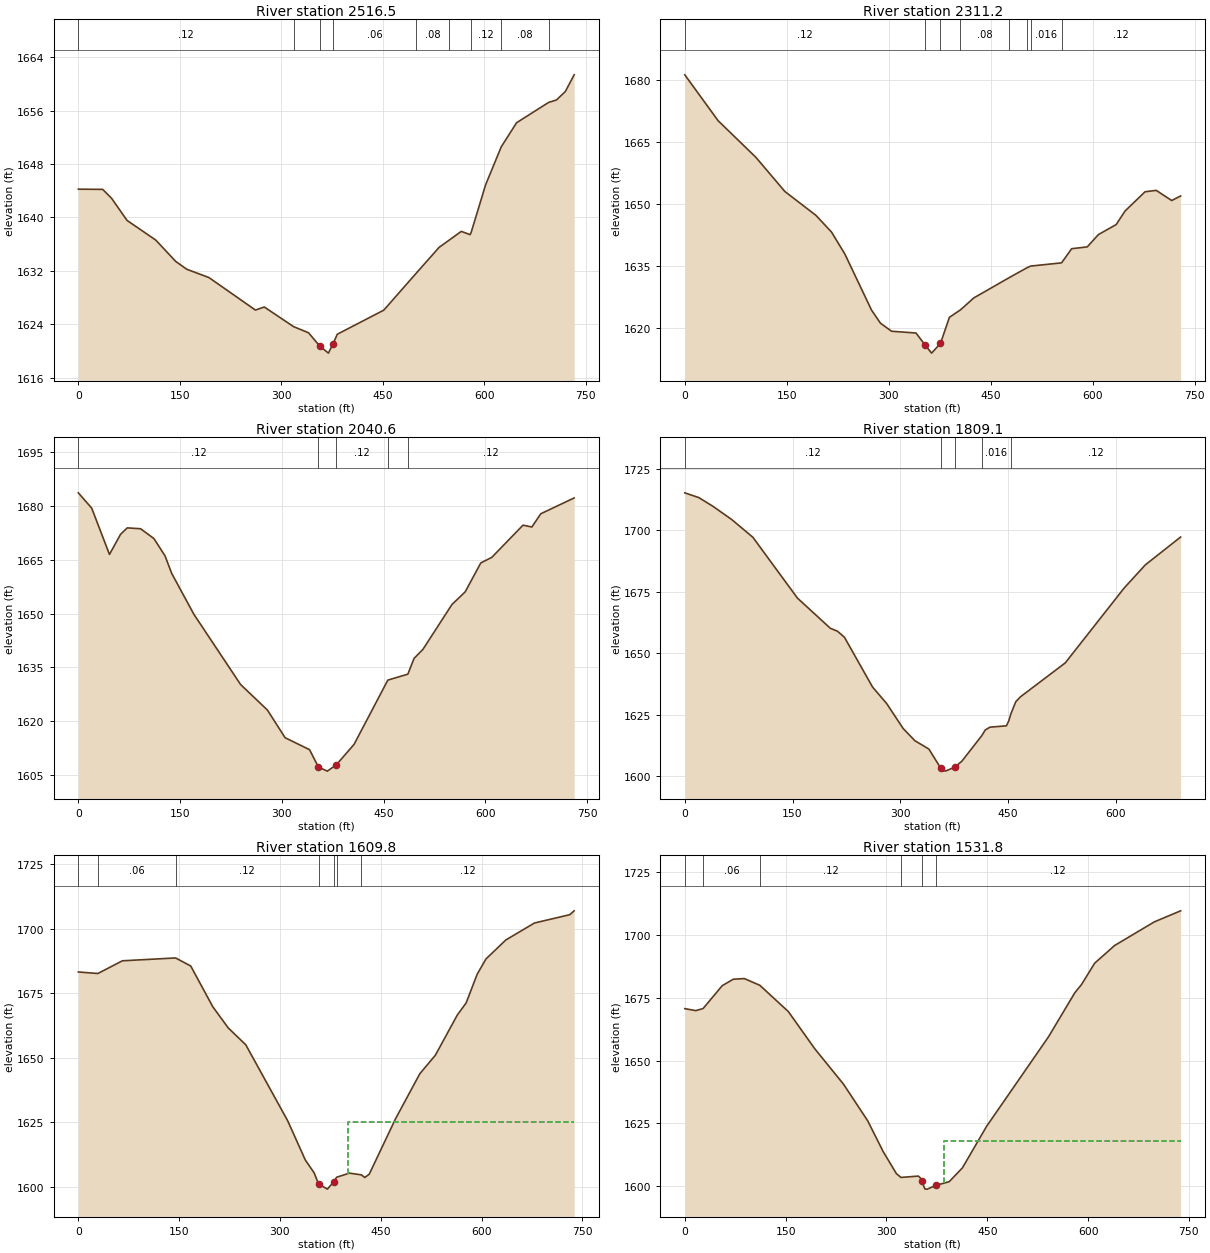
Type RM Length L Ch R = 1 ,2516.5  ,211.2,205.3,197.8
XS GIS Cut Line= 2
     2058371.699      195012.339     2059103.995      194988.246
#Sta/Elev= 30
       0 1644.22      36 1644.19    49.1 1642.86      72 1639.54   114.5 1636.59
   143.9  1633.4   160.3 1632.22     193 1630.98   261.7 1626.11   274.8 1626.57
  318.121623.625   340.2 1622.71   356.5 1620.74   369.6 1619.66   376.2 1621.03
   382.7 1622.49   451.4  1626.1  499.361631.636   533.2 1635.51  547.181636.526
   565.9  1637.9     579 1637.41  580.531637.754   601.8 1644.86  624.921650.555
   647.6 1654.17  694.951657.216   706.5 1657.58   719.6 1658.84   732.7 1661.35
#Mann= 9 ,-1 , 0
       0     .12       0  318.12     .06       0   356.5    .045       0
   376.2     .06       0  499.36     .08       0  547.18    .016       0
  580.53     .12       0  624.92     .08       0  694.95     .06       0
Bank Sta=356.5,376.2
XS Rating Curve= 0 ,0
Exp/Cntr=0.3,0.1

Type RM Length L Ch R = 1 ,2311.2  ,273.8,270.6,267
XS GIS Cut Line= 2
     2058436.862      195307.907     2059127.673      195074.641
#Sta/Elev= 30
       0 1681.33      49 1670.22   104.6 1661.34   147.1 1653.09   192.9 1647.29
   215.8 1643.24   235.4 1637.92   274.6 1624.35   287.7 1621.18   304.1 1619.23
     340  1618.8   353.1 1615.95   362.9 1613.93     376 1616.29   389.1  1622.6
  405.341624.404     425  1627.3  477.251632.232  502.751634.565  508.431635.009
  554.021635.792   568.9 1639.22   591.8 1639.66   608.2 1642.64   634.3 1645.06
   647.4 1648.35   676.8 1653.01   693.2 1653.35     716 1650.89   729.1 1651.99
#Mann= 8 ,-1 , 0
       0     .12       0   353.1    .045       0     376     .06       0
  405.34     .08       0  477.25     .12       0  502.75     .08       0
  508.43    .016       0  554.02     .12       0
Bank Sta=353.1,376
XS Rating Curve= 0 ,0
Exp/Cntr=0.3,0.1

Type RM Length L Ch R = 1 ,2040.6  ,233,231.5,229.9
XS GIS Cut Line= 2
     2058544.426      195601.635     2059199.997      195278.692
#Sta/Elev= 30
       0 1683.73    19.7 1679.46    45.9 1666.53    62.3 1672.16    72.1 1673.94
    91.8  1673.7   111.4 1670.96   127.8 1666.12   137.6 1661.24   170.4 1649.78
   239.2 1630.19   278.6 1623.09   304.8 1615.34   340.8    1612   353.9 1607.14
     367 1606.01   380.2 1607.76   406.4 1613.48  456.191631.432   485.7 1633.09
   494.8 1637.48     508 1640.04   550.6 1652.52   570.2 1656.08   593.2 1664.15
   609.5 1665.72   655.4  1674.7   668.5 1674.19   681.6 1677.88   730.8  1682.3
#Mann= 5 ,-1 , 0
       0     .12       0   353.9    .045       0   380.2     .12       0
  456.19    .016       0   485.7     .12       0
Bank Sta=353.9,380.2
XS Rating Curve= 0 ,0
Exp/Cntr=0.3,0.1

Type RM Length L Ch R = 1 ,1809.1  ,203.8,199.3,194.9
XS GIS Cut Line= 3
     2058621.057       195842.88     2059022.508      195610.158
     2059238.654      195543.751
#Sta/Elev= 30
       0 1715.14    19.6 1713.19    39.2 1709.67    65.4 1704.28    94.8 1697.09
   156.8 1672.41   202.6 1660.16   212.4 1658.99   222.2 1656.53   261.4 1636.29
     281 1629.61   303.9  1619.5   320.2 1614.54   339.8 1611.12   356.4 1603.32
   362.7 1602.17   375.8 1603.78   385.6 1606.18  413.261616.505   418.3  1618.9
   424.8 1620.01   447.7 1620.56     451  1622.6  454.051625.517   460.8 1630.38
   467.3 1632.35   529.6  1646.1   611.5 1676.46     641 1685.88   690.2  1697.2
#Mann= 5 ,-1 , 0
       0     .12       0   356.4    .045       0   375.8     .12       0
  413.26    .016       0  454.05     .12       0
Bank Sta=356.4,375.8
XS Rating Curve= 0 ,0
Exp/Cntr=0.3,0.1

Type RM Length L Ch R = 1 ,1609.8  ,77.4,77.9,77.7
XS GIS Cut Line= 2
     2058762.062      196073.137     2059316.731      195586.764
#Sta/Elev= 30
       0 1683.19   29.12 1682.61    65.6 1687.53  144.67 1688.63   167.2 1685.52
     200 1669.75     223 1661.53   249.2 1654.96   311.5 1625.54   337.7 1610.36
   350.8 1605.39   357.4 1601.08   370.5 1599.06   380.3 1601.98  384.261603.656
   403.3 1605.26     4211604.597   426.2 1603.58   432.8 1604.84   472.1  1626.4
   508.2 1643.82   531.2 1650.94   563.9 1666.54     577 1671.21   593.4 1682.32
   606.6 1688.28   636.1 1695.61   678.7 1702.18   731.2 1705.39   737.7 1706.89
#Mann= 7 ,-1 , 0
       0     .12       0   29.12     .06       0  144.67     .12       0
   357.4    .045       0   380.3     .12       0  384.26    .016       0
     421     .12       0
#XS Ineff= 2 , 0
                          400.68         1625.17
Permanent Ineff=
       F       F
Bank Sta=357.4,380.3
XS Rating Curve= 0 ,0
Exp/Cntr=0.3,0.1

Type RM Length L Ch R = 1 ,1531.8  ,165.5,171.7,176.7
XS GIS Cut Line= 2
     2058818.312      196121.835     2059372.981      195635.462
#Sta/Elev= 30
       0 1670.73    16.4 1669.94   27.241670.775    55.7 1679.88    72.1 1682.44
    88.5 1682.71  111.661680.028   154.1 1669.55   193.4 1654.75   236.1 1640.66
   272.1 1626.08   295.1 1613.81   314.8 1605.02  321.561603.496   347.5 1604.04
   350.8 1603.21  352.44  1601.9   357.4 1598.88   360.7 1598.84   373.8 1600.34
   393.4 1601.81   413.1 1607.33   449.2 1623.93     541 1659.45   580.3 1677.06
   590.2 1680.31   609.8 1688.83   639.4 1695.86   698.4 1705.26   737.7 1709.69
#Mann= 6 ,-1 , 0
       0     .12       0   27.24     .06       0  111.66     .12       0
  321.56    .016       0  352.44    .045       0   373.8     .12       0
#XS Ineff= 2 , 0
                           385.3         1617.83
Permanent Ineff=
       F       F
Bank Sta=352.44,373.8
XS Rating Curve= 0 ,0
Exp/Cntr=0.3,0.1

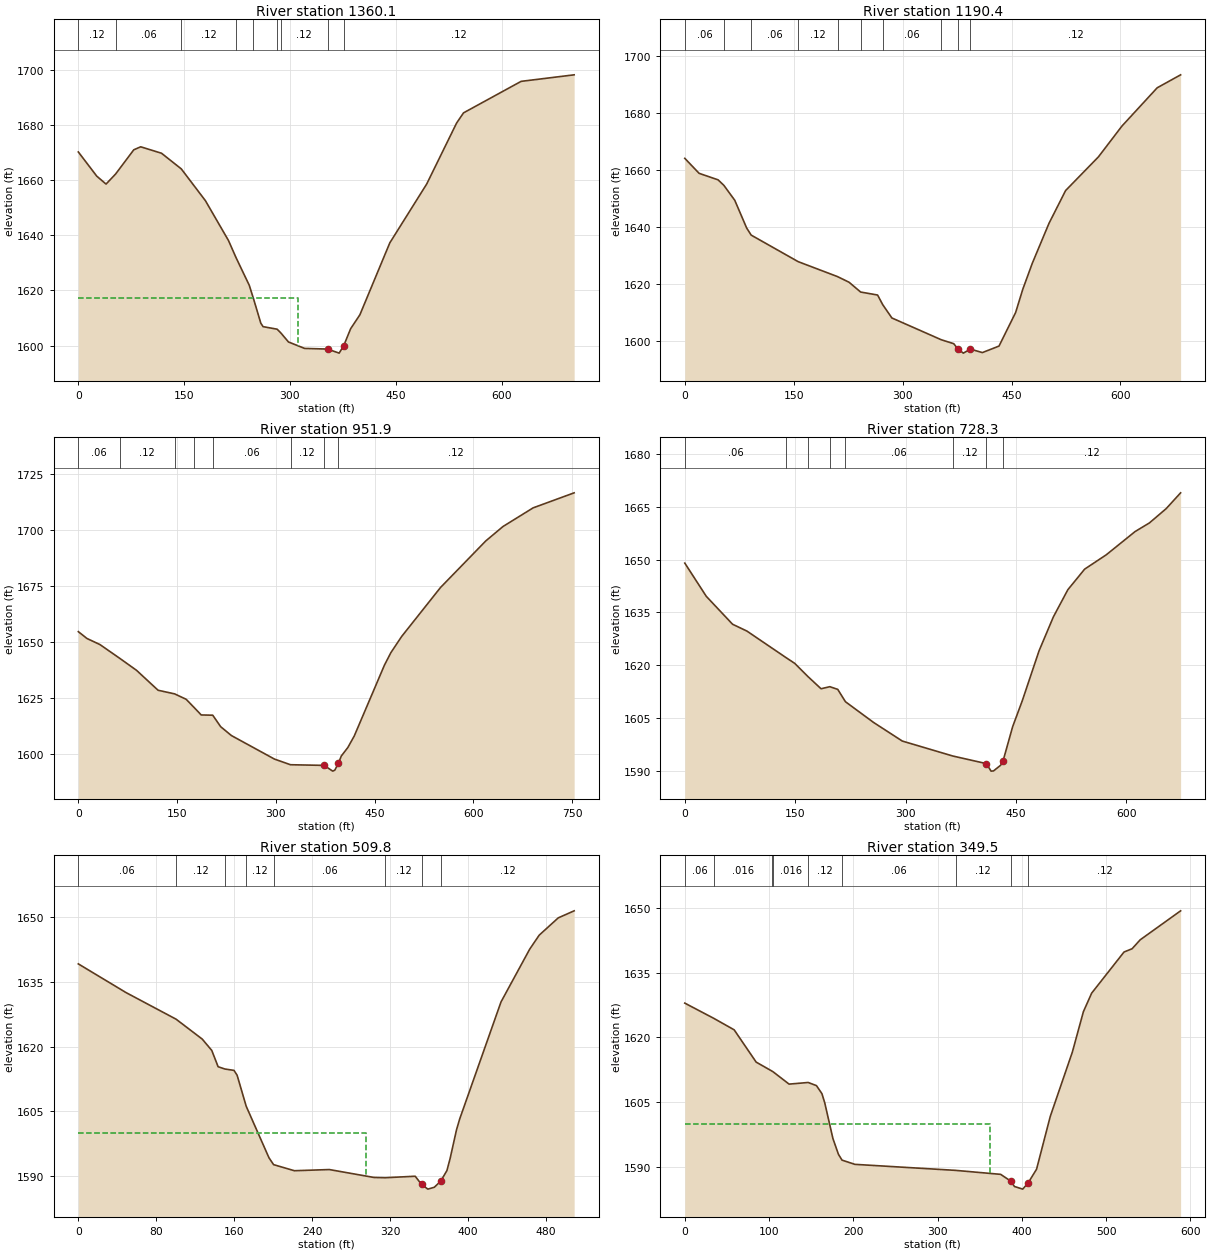
Type RM Length L Ch R = 1 ,1360.1  ,169.2,169.8,175.9
XS GIS Cut Line= 3
     2058831.326      196164.139     2059076.284      196081.034
      2059469.34       195874.35
#Sta/Elev= 30
       0 1670.18    26.2 1661.39    39.3 1658.54   52.751662.159    78.6 1670.96
    88.4 1672.05   117.9 1669.72  145.961664.035   180.1 1652.53   212.8 1638.09
  223.571631.856   242.3 1621.83  248.041617.187   258.7 1608.07   261.9 1606.84
  281.781605.915   287.2 1604.52   297.9 1601.28   320.7 1598.95   353.4 1598.71
   369.7 1597.24   376.2 1599.96     386  1606.1   399.1 1611.15   441.5 1637.22
   493.8 1658.56   536.2 1680.68     546 1684.36   627.6 1695.78   702.8 1698.15
#Mann= 9 ,-1 , 0
       0     .12       0   52.75     .06       0  145.96     .12       0
  223.57     .08       0  248.04    .016       0  281.78     .06       0
   287.2     .12       0   353.4    .045       0   376.2     .12       0
#XS Ineff= 2 , 0
          310.68 1617.14
Permanent Ineff=
       F       F
Bank Sta=353.4,376.2
XS Rating Curve= 0 ,0
Exp/Cntr=0.3,0.1

Type RM Length L Ch R = 1 ,1190.4  ,230.3,238.5,242.1
XS GIS Cut Line= 3
     2058881.238      196367.173     2059342.899      196125.242
     2059410.616      195978.517
#Sta/Elev= 30
       0    1664    19.7 1658.75    45.9 1656.46   53.881654.513    68.8 1649.31
    85.2 1639.59   91.42 1637.11  156.111627.812  210.33 1622.57   226.2  1620.6
  242.181617.164   265.5 1616.12  272.641612.714   285.2 1608.08  353.131600.464
   370.4 1599.07   375.6 1597.38   383.5 1595.77   393.4 1597.17   409.8 1595.96
   432.7 1598.24   455.6    1610   465.5 1618.18   478.6 1627.28   501.5 1641.21
   524.4 1652.71   569.7 1664.54     602  1675.3   650.5  1688.7   682.8 1693.25
#Mann= 10 ,-1 , 0
       0     .06       0   53.88     .12       0   91.42     .06       0
  156.11     .12       0  210.33     .08       0  242.18    .016       0
  272.64     .06       0  353.13     .12       0   375.6    .045       0
   393.4     .12       0
Bank Sta=375.6,393.4
XS Rating Curve= 0 ,0
Exp/Cntr=0.3,0.1

Type RM Length L Ch R = 1 ,951.9   ,226.6,223.6,219.7
XS GIS Cut Line= 2
     2058951.908      196443.133     2059692.617      196306.151
#Sta/Elev= 30
       0 1654.51    13.1 1651.47    32.8 1648.76   63.411642.513    88.4 1637.27
   121.2 1628.37  146.271626.765   163.8 1624.35  176.311620.565   186.7 1617.36
  204.191617.254   216.2 1612.14   232.5 1608.19     298 1597.68  322.361595.162
   373.4 1594.87   386.5 1592.31   389.7 1592.75   394.9 1595.73   399.6 1599.08
   409.4 1602.81   419.2 1607.97   465.1  1639.6   474.9 1645.17   491.3 1652.39
   550.2 1674.18     619 1694.96   645.2  1701.4     691 1709.72   753.3 1716.42
#Mann= 8 ,-1 , 0
       0     .06       0   63.41     .12       0  146.27     .08       0
  176.31    .016       0  204.19     .06       0  322.36     .12       0
   373.4    .045       0   394.9     .12       0
Bank Sta=373.4,394.9
XS Rating Curve= 0 ,0
Exp/Cntr=0.3,0.1

Type RM Length L Ch R = 1 ,728.3   ,217.3,218.4,219
XS GIS Cut Line= 3
     2058959.965      196578.213     2059252.196      196621.963
     2059611.007      196502.692
#Sta/Elev= 30
       0 1648.99    29.2 1639.55    64.9 1631.62    84.4 1629.68  137.281622.179
   149.4  1620.5  167.151616.792   185.1  1613.3  197.021613.883   207.8 1613.12
  218.251609.612   256.5 1603.72   295.5 1598.44  364.14 1594.19   409.6 1592.04
   416.1  1589.9   419.4 1589.96   429.1 1591.57   432.4 1592.82   445.4 1602.52
   458.5  1609.9   481.3 1624.09   500.8 1633.74   520.4 1641.43   543.2 1647.27
   572.6 1651.35   611.7 1657.94   631.2  1660.4     654 1664.46   673.6 1668.95
#Mann= 8 ,-1 , 0
       0     .06       0  137.28     .12       0  167.15     .08       0
  197.02    .016       0  218.25     .06       0  364.14     .12       0
   409.6    .045       0   432.4     .12       0
Bank Sta=409.6,432.4
XS Rating Curve= 0 ,0
Exp/Cntr=0.3,0.1

Type RM Length L Ch R = 1 ,509.8   ,171.8,160.3,148.9
XS GIS Cut Line= 3
     2059034.097      196849.828     2059255.581      196838.977
     2059531.059      196757.597
#Sta/Elev= 30
       0 1639.21    48.9 1632.56  100.361626.377   127.2 1621.76     137 1619.13
   143.5 1615.35  150.42 1614.82   159.8  1614.5     163 1613.38  172.32 1606.19
   195.7 1594.23  200.45 1592.63   221.8 1591.22   257.7 1591.49   303.4 1589.66
  315.091589.594   345.8 1589.94   352.3 1588.05   358.8 1586.95   365.4 1587.38
   371.9 1588.77   378.4 1591.26   381.7 1594.09   388.2 1600.69   391.5 1603.23
   433.9 1630.38   463.3  1642.6   473.1 1645.87   492.7 1649.89     509 1651.52
#Mann= 8 ,-1 , 0
       0     .06       0  100.36     .12       0  150.42    .016       0
  172.32     .12       0  200.45     .06       0  315.09     .12       0
   352.3    .045       0   371.9     .12       0
#XS Ineff= 2 , 0
          295.42  1599.9
Permanent Ineff=
       F       F
Bank Sta=352.3,371.9
XS Rating Curve= 0 ,0
Exp/Cntr=0.3,0.1

Type RM Length L Ch R = 1 ,349.5   ,218.1,222.9,223.8
XS GIS Cut Line= 4
     2059097.031       197034.29     2059370.468      197026.694
     2059517.597      196877.784      2059552.76      196778.213
#Sta/Elev= 30
       0 1627.92   34.591624.367    58.6 1621.72    84.7 1614.23  103.271612.163
  104.971611.957   123.8 1609.12  146.431609.502   156.3 1608.77   162.8 1606.89
   166.1 1604.79   175.8  1596.5   182.4 1592.81  186.651591.478   201.9  1590.5
  321.311589.104   374.9 1588.18   386.7 1586.63   391.3 1585.36   401.1 1584.75
   407.6 1586.22   417.5 1589.37   433.8 1601.64     460 1616.56   473.1 1625.93
   482.9 1630.23   521.3 1639.78   530.9 1640.54   540.5 1642.61   588.5 1649.34
#Mann= 9 ,-1 , 0
       0     .06       0   34.59    .016       0  103.27     .06       0
  104.97    .016       0  146.43     .12       0  186.65     .06       0
  321.31     .12       0   386.7    .045       0   407.6     .12       0
#XS Ineff= 2 , 0
           361.9 1599.92
Permanent Ineff=
       F       F
Bank Sta=386.7,407.6
XS Rating Curve= 0 ,0
Exp/Cntr=0.3,0.1

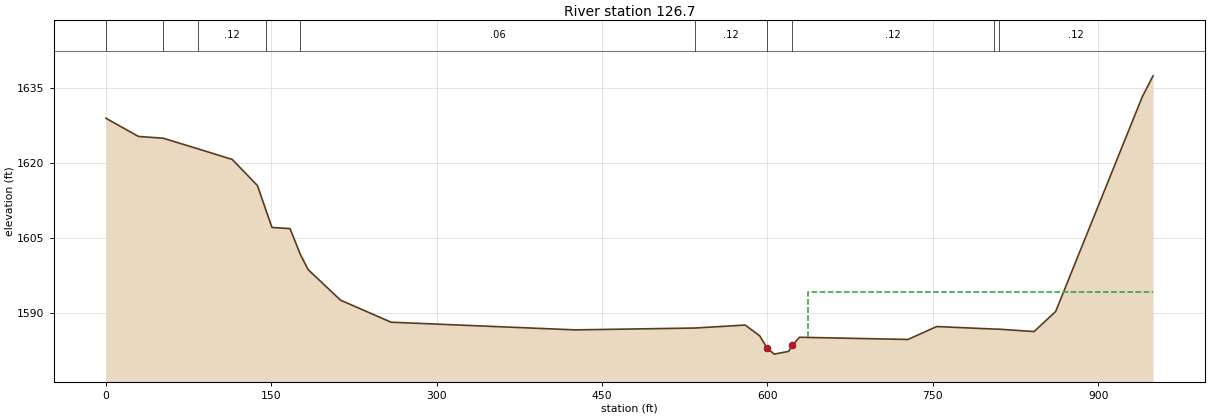
Type RM Length L Ch R = 1 ,126.7   ,146.3,126.7,105.3
XS GIS Cut Line= 4
     2059075.633      197063.673     2059480.408      197195.531
     2059699.679      197013.022     2059671.033      196776.043
#Sta/Elev= 30
       0 1629.01    29.5 1625.36   52.091624.995   83.25 1622.89   114.6 1620.74
   137.5 1615.49  145.381610.421   150.6 1607.11     167 1606.88  176.451601.659
   183.4 1598.66   212.8 1592.53   258.7 1588.11   425.7 1586.57  534.491586.944
   579.8 1587.54     593 1585.37   599.5 1582.99   606.1 1581.71   619.2 1582.26
   622.5 1583.45     629 1585.09   727.4 1584.65   753.5 1587.24  805.79 1586.73
  809.971586.715   841.8 1586.23   861.4 1590.27   939.9 1633.29   949.7 1637.51
#Mann= 10 ,-1 , 0
       0    .016       0   52.09     .06       0   83.25     .12       0
  145.38    .016       0  176.45     .06       0  534.49     .12       0
   599.5    .045       0   622.5     .12       0  805.79     .06       0
  809.97     .12       0
#XS Ineff= 2 , 0
                          637.08         1594.21
Permanent Ineff=
       F       F
Bank Sta=599.5,622.5
XS Rating Curve= 0 ,0
Exp/Cntr=0.3,0.1

Chan Stop Cuts=-1
Use User Specified Reach Order=0
Composite Channel Slope=5